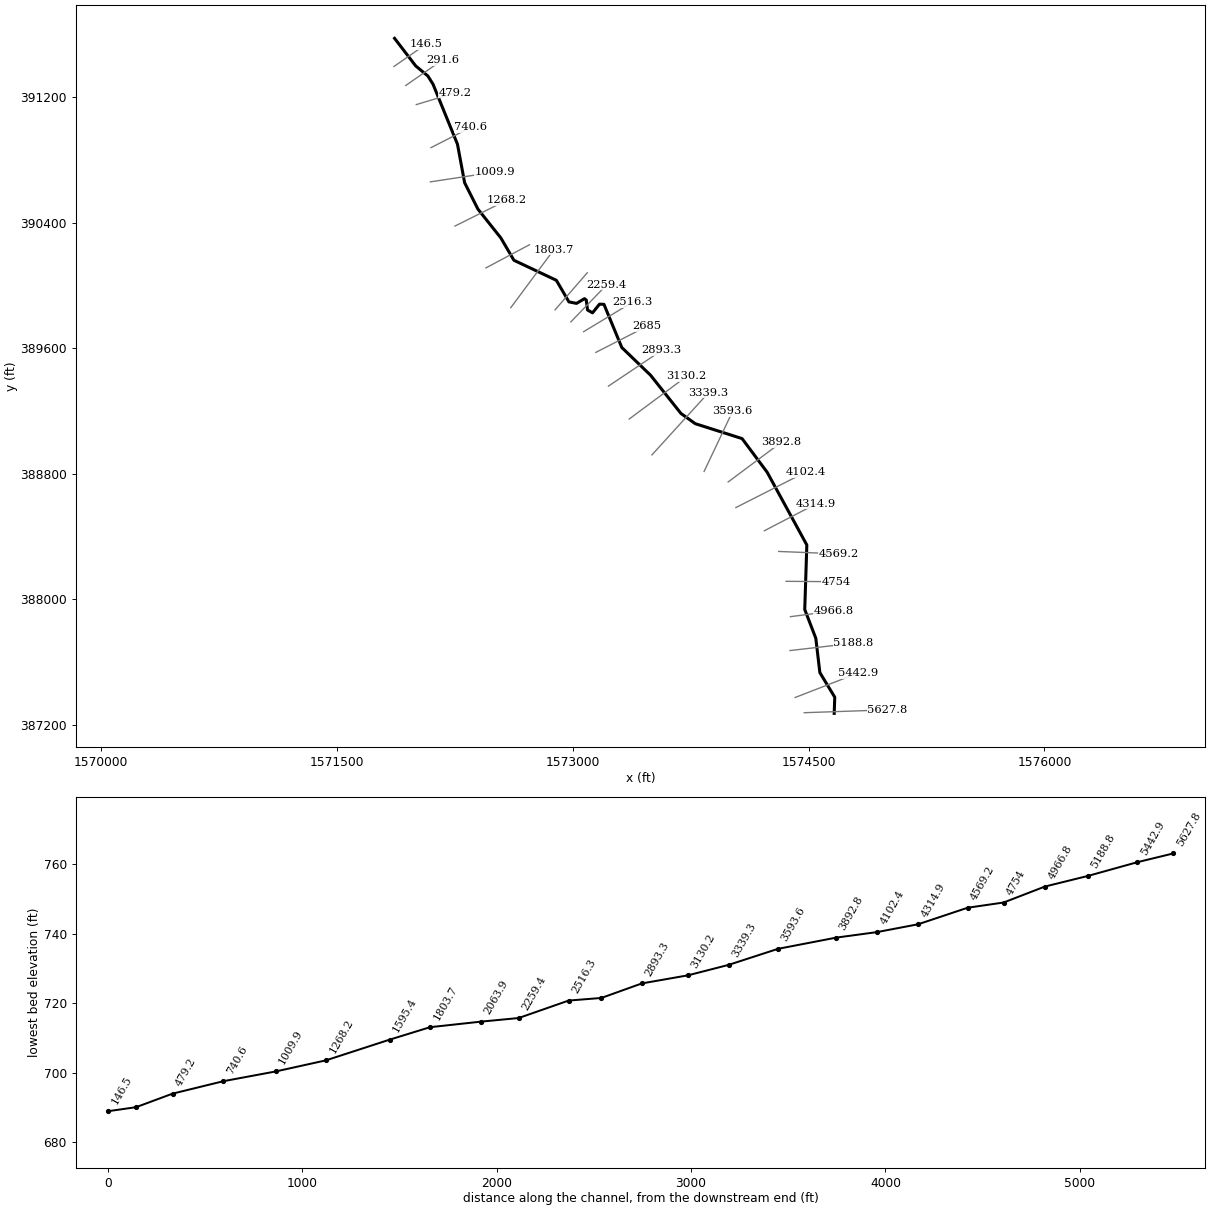
--- LFRICHCR.prj (project) ---

Proj Title=LFRICHCR
Current Plan=p01
Default Exp/Contr=0,0
English Units
Geom File=g01
Flow File=f01
Plan File=p01
BEGIN DESCRIPTION:
END DESCRIPTION:
DSS Export Rating Curves= 0
DSS Export Rating Curve Sorted= 0
DSS Export Volume Flow Curves= 0
DXF OffsetX= 0
DXF OffsetY= 0
DXF ScaleX= 0
DXF ScaleY= 0

--- LFRICHCR.p01 (plan) ---

Plan Title=Floodplain
Program Version=4.00
Geom File=g01
Flow File=f01
K Sum by GR=0
Std Step Tol=0.01
Critical Tol=0.01
Num of Std Step Trials=20
Max Error Tol=0.3
Flow Tol Ratio=0.001
Split Flow NTrial=30
Split Flow Tol=0.02
Split Flow Ratio=0.02
Log Output Level=0
Friction Slope Method=1
Unsteady Friction Slope Method=2
Unsteady Bridges Friction Slope Method=1
Global Log Level=0
CheckData=False
Run HTab=0
Run UNet=0
Run PostProcess=0
UNET Theta=0
UNET Theta Warmup=0
UNET ZTol=0
UNET ZSATol=0
UNET MxIter=0
UNET MaxInSteps=0
UNET DtIC=0
UNET DtMin=0
UNET MaxCRTS=0
UNET WFStab=0
UNET SFStab=0
UNET WFX=0
UNET SFX=0
UNET DSS MLevel=0
UNET DZMax Abort=0
UNET Convert EG Bridges=0
UNET Use Existing IB Tables=0
UNET Froude Limit=0
UNET Froude Power=0
Write IC File=0
Echo Input=False
Echo Output=False
Write Detailed=0

--- LFRICHCR.f01 (steady flow) ---

Flow Title=NFF Regression Equation
Program Version=4.00
Number of Profiles=1
Profile Names=P100yr
River Rch & RM=LFRICHCR,Main      ,5627.8
378.7352
River Rch & RM=LFRICHCR,Main      ,3892.8
407.0928
River Rch & RM=LFRICHCR,Main      ,3593.6
500.5181
River Rch & RM=LFRICHCR,Main      ,2685
521.7812
River Rch & RM=LFRICHCR,Main      ,291.6
579.4121
Boundary for River Rch & Prof#=LFRICHCR,Main      ,1
Up Type=0
Dn Type=3
Dn Slope=0.014181

--- LFRICHCR.g01 (geometry) ---

Geom Title=Geometry
Program Version=4.00

River Reach=LFRICHCR        ,Main
Reach XY= 30
      1574662.99      387273.983     1574666.537      387376.923
     1574571.828      387533.998     1574545.999      387752.756
     1574475.716      387935.906     1574488.885      388347.129
     1574236.902      388810.253     1574077.069      389025.009
     1573779.301      389120.011     1573688.505      389185.152
     1573495.269      389428.672     1573312.531      389605.126
     1573198.789      389880.621     1573170.614      389881.527
     1573126.307      389826.323     1573094.713      389844.069
     1573086.255       389908.48     1573074.983      389916.522
     1573024.435       389886.38     1572976.166      389896.131
     1572896.293      390033.518     1572626.249      390161.334
     1572543.407      390303.406     1572397.474      390487.258
     1572312.992       390655.24     1572267.454      390900.728
     1572111.649      391283.935     1572078.875      391335.766
     1572001.733      391399.794     1571867.464      391575.417

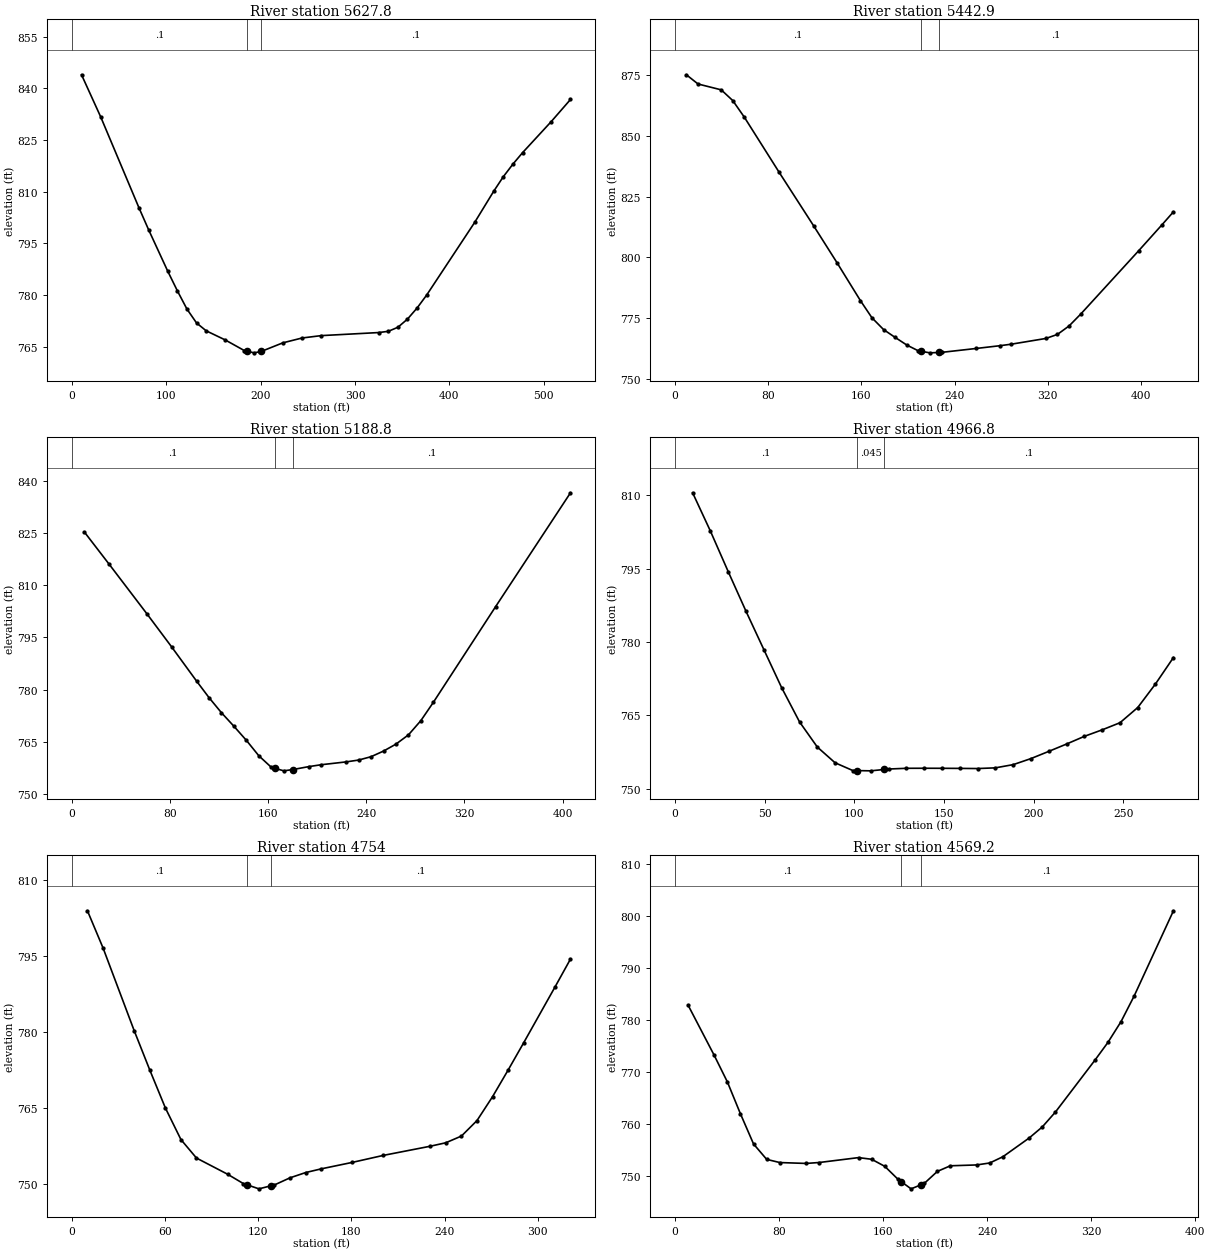
Type RM Length L Ch R = 1 ,5627.8  ,177.4,185,192.6
XS GIS Cut Line= 2
     1574472.662      387278.243     1575000.719      387296.362
#Sta/Elev= 30
    10.2  843.94    30.5  831.72    71.1  805.29    81.3  798.93   101.6  786.88
   111.8  781.18   121.9  775.91   132.1  771.86   142.3  769.59   162.6  766.92
   182.9  763.82   185.6  763.66   193.1  763.19   200.6  763.59   223.5  766.09
   243.9   767.5   264.2  768.19   325.1  769.08   335.3  769.44   345.5  770.62
   355.6  772.98   365.8   776.2     376  779.98   426.8  801.05   447.1  810.15
   457.2  814.34   467.4     818   477.6  821.32     508  830.35   528.4  836.77
#Mann= 3 , 0 , 0
       0      .1       0   185.6    .045       0   200.6      .1       0
Bank Sta=185.6,200.6
XS Rating Curve= 0 ,0
Exp/Cntr=0.3,0.1

Type RM Length L Ch R = 1 ,5442.9  ,259.8,254,248.3
XS GIS Cut Line= 2
     1574414.472      387374.989     1574813.103        387530.3
#Sta/Elev= 28
     9.9  875.23    19.9  871.43    39.8  869.02    49.7   864.6    59.7   857.7
    89.5  835.04   119.4  812.76   139.3  797.68   159.2   782.2   169.1  775.12
   179.1  770.25     189  767.03     199  763.89   208.9   761.5   211.4  761.29
   218.9  760.67   226.4  760.81   228.8  760.86   258.7  762.48   278.6  763.59
   288.5  764.22   318.4   766.6   328.3  768.27   338.3  771.77   348.2  776.61
     398  802.75   417.9  813.39   427.8  818.77
#Mann= 3 , 0 , 0
       0      .1       0   211.4    .045       0   226.4      .1       0
Bank Sta=211.4,226.4
XS Rating Curve= 0 ,0
Exp/Cntr=0.3,0.1

Type RM Length L Ch R = 1 ,5188.8  ,221.7,222,222.4
XS GIS Cut Line= 2
     1574382.064      387674.285     1574785.872      387720.879
#Sta/Elev= 26
    10.2  825.24    30.5  815.95      61  801.85    81.3  792.29   101.6  782.49
   111.8  777.72   121.9   773.4   132.1   769.5   142.3  765.44   152.4  761.03
   162.6  757.72   165.3  757.45   172.8  756.71   180.3  757.09   193.1  757.92
   203.2  758.46   223.6  759.28   233.7   759.8   243.9  760.77   254.1  762.39
   264.2  764.38   274.4  767.04   284.5  771.12   294.7  776.38   345.5  803.87
   406.5  836.52
#Mann= 3 , 0 , 0
       0      .1       0   165.3    .045       0   180.3      .1       0
Bank Sta=165.3,180.3
XS Rating Curve= 0 ,0
Exp/Cntr=0.3,0.1

Type RM Length L Ch R = 1 ,4966.8  ,215.9,212.8,209.7
XS GIS Cut Line= 2
     1574384.678      387890.192     1574660.196      387926.221
#Sta/Elev= 30
     9.9  810.52    19.8   802.7    29.8  794.34    39.7  786.25    49.6  778.45
    59.5  770.67    69.5  763.65    79.4  758.51    89.3  755.29    99.2   753.7
   101.7  753.69   109.2  753.64   116.7  753.92   119.1  754.01     129  754.16
   138.9  754.17   148.9  754.16   158.8  754.14   168.7  754.11   178.6  754.25
   188.6  754.91   198.5  756.15   208.4  757.62   218.3  759.12   228.2  760.69
   238.2  762.03   248.1  763.48     258  766.59   267.9  771.42   277.9  776.82
#Mann= 3 , 0 , 0
       0      .1       0   101.7    .045       0   116.7      .1       0
Bank Sta=101.7,116.7
XS Rating Curve= 0 ,0
Exp/Cntr=0.3,0.1

Type RM Length L Ch R = 1 ,4754    ,185.6,184.8,184.1
XS GIS Cut Line= 2
     1574357.072      388115.497     1574678.048      388112.909
#Sta/Elev= 27
      10  803.85    20.1  796.48    40.1  780.21    50.2  772.41    60.2  764.96
    70.2  758.74    80.2   755.1   100.3   751.9   110.3  750.08   112.9  749.81
   120.4  749.03   127.9  749.61   130.4   749.8   140.4   751.2   150.5  752.24
   160.5  752.97   180.6  754.25   200.6  755.63   230.7  757.43   240.7  758.11
   250.8  759.44   260.8  762.49   270.8  767.19   280.9  772.48   290.9  777.85
     311  788.81     321  794.34
#Mann= 3 , 0 , 0
       0      .1       0   112.9    .045       0   127.9      .1       0
Bank Sta=112.9,127.9
XS Rating Curve= 0 ,0
Exp/Cntr=0.3,0.1

Type RM Length L Ch R = 1 ,4569.2  ,242.6,254.3,266
XS GIS Cut Line= 2
     1574309.652        388305.8     1574692.686      388290.352
#Sta/Elev= 30
    10.1  782.85    30.3  773.16    40.4  768.06    50.4  761.96    60.5  756.15
    70.6  753.19    80.7  752.58   100.9  752.41     111  752.59   141.2  753.53
   151.3  753.21   161.4  751.85   171.5  749.38   174.1   748.9   181.6  747.53
   189.1  748.29   191.7  748.56   201.8  750.88   211.8  751.96     232  752.12
   242.1   752.5   252.2   753.7   272.4   757.3   282.5  759.43   292.6  762.29
   322.8   772.2   332.9  775.65     343  779.65   353.1  784.58   383.3  800.95
#Mann= 3 , 0 , 0
       0      .1       0   174.1    .045       0   189.1      .1       0
Bank Sta=174.1,189.1
XS Rating Curve= 0 ,0
Exp/Cntr=0.3,0.1

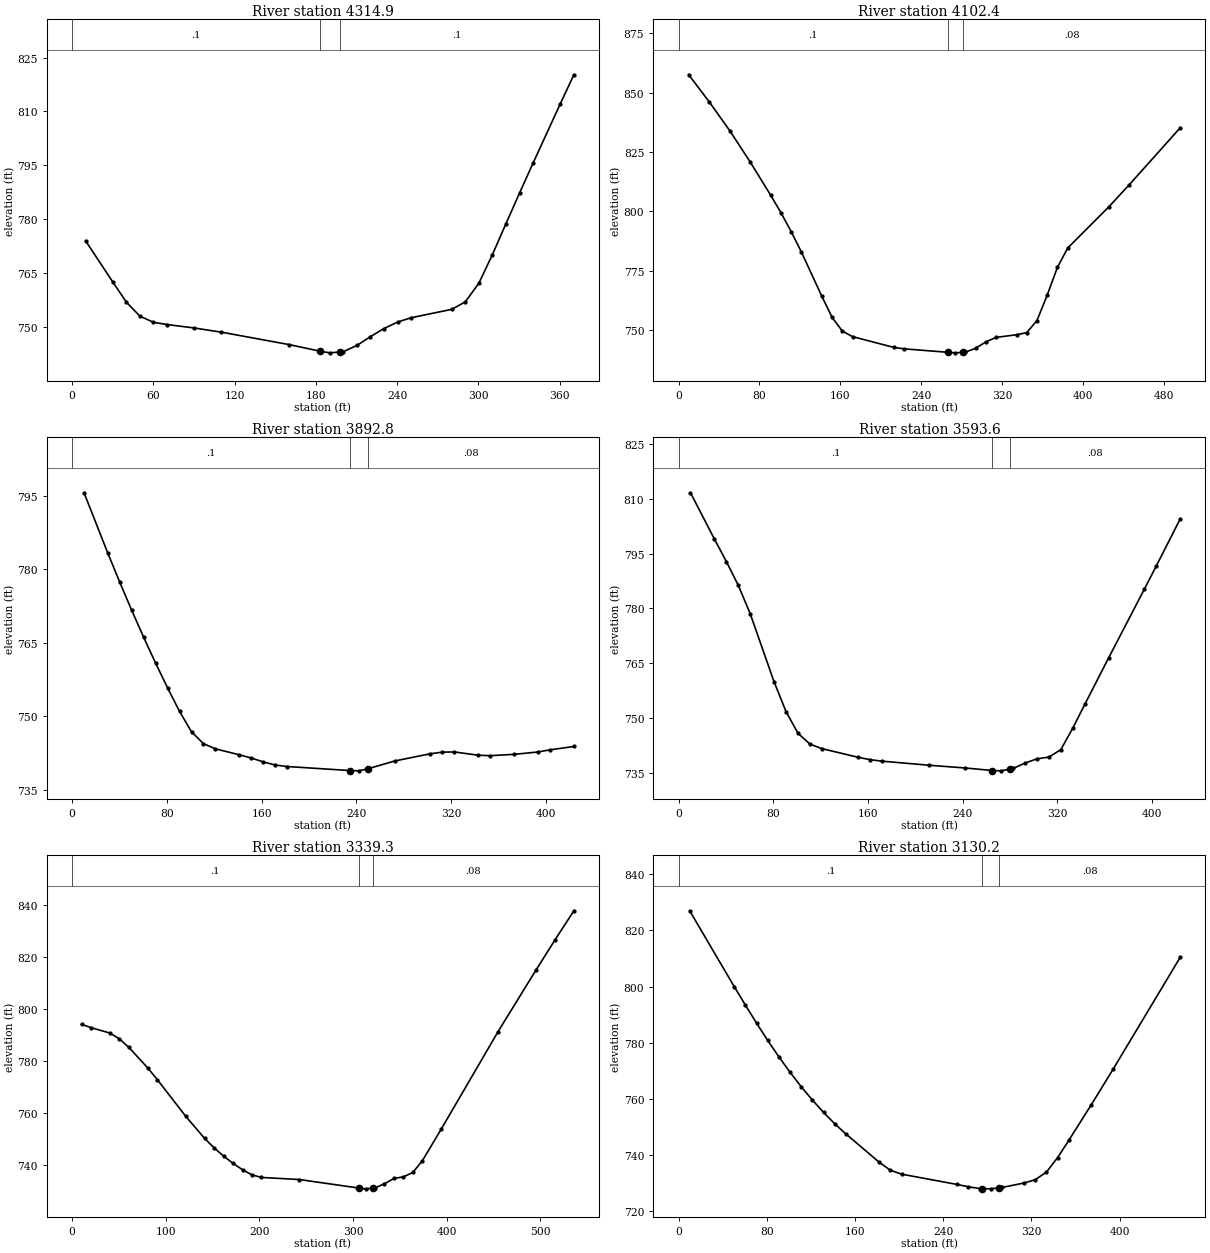
Type RM Length L Ch R = 1 ,4314.9  ,212.7,212.5,212.3
XS GIS Cut Line= 2
     1574218.988      388437.897     1574547.729      388608.739
#Sta/Elev= 27
      10  773.96      30  762.54    40.1  756.89    50.1  752.98    60.1  751.28
    70.1  750.65    90.1   749.7   110.1  748.54   160.2  745.07   182.7  743.26
   190.2  742.77   197.7  743.01   200.3   743.1   210.3  744.82   220.3  747.28
   230.3  749.54   240.3  751.33   250.3  752.54   280.4  754.89   290.4  756.98
   300.4   762.2   310.4  770.15   320.4  778.77   330.4  787.27   340.4  795.63
   360.5  812.15   370.5  820.21
#Mann= 3 , 0 , 0
       0      .1       0   182.7    .045       0   197.7      .1       0
Bank Sta=182.7,197.7
XS Rating Curve= 0 ,0
Exp/Cntr=0.3,0.1

Type RM Length L Ch R = 1 ,4102.4  ,205.7,209.6,213.5
XS GIS Cut Line= 2
     1574037.792      388585.442     1574480.428      388810.643
#Sta/Elev= 30
    10.1  857.47    30.4  846.08    50.7  833.95    70.9   820.8    91.2   806.8
   101.4  799.41   111.5  791.49   121.6   782.9   141.9  764.22     152  755.39
   162.2  749.62   172.3  747.31   212.8  742.81     223  742.19   266.2  740.74
   273.7   740.5   281.2   740.7   283.8  740.78   293.9   742.4   304.1  745.07
   314.2     747   334.5  748.11   344.6     749   354.7  754.08   364.9  764.82
     375  776.48   385.1  784.56   425.7  801.86     446  811.19   496.6  835.22
#Mann= 3 , 0 , 0
       0      .1       0   266.2    .045       0   281.2     .08       0
Bank Sta=266.2,281.2
XS Rating Curve= 0 ,0
Exp/Cntr=0.3,0.1

Type RM Length L Ch R = 1 ,3892.8  ,288.2,299.2,310.2
XS GIS Cut Line= 2
      1573988.61      388748.518     1574327.706      389002.193
#Sta/Elev= 29
    10.1  795.56    30.2  783.24    40.3  777.31    50.4  771.58    60.5  766.08
    70.6  760.81    80.7  755.77    90.7  751.02   100.8  746.86   110.9  744.45
     121  743.39   141.2  742.18   151.2  741.52   161.3  740.74   171.4   740.1
   181.5  739.79   234.5  738.97     242  738.91   249.5  739.32   272.2  740.91
   302.5   742.4   312.6  742.72   322.7  742.76   342.8  742.09   352.9     742
   373.1  742.27   393.2  742.75   403.3  743.19   423.5  743.87
#Mann= 3 , 0 , 0
       0      .1       0   234.5    .045       0   249.5     .08       0
Bank Sta=234.5,249.5
XS Rating Curve= 0 ,0
Exp/Cntr=0.3,0.1

Type RM Length L Ch R = 1 ,3593.6  ,260.9,254.2,247.6
XS GIS Cut Line= 2
     1573835.888       388815.82     1574017.084       389198.92
#Sta/Elev= 29
    10.1  811.58    30.3  798.95    40.4   792.8    50.5   786.3    60.5  778.59
    80.7  759.96    90.8  751.85   100.9  745.94     111  742.97   121.1  741.74
   151.4   739.4   161.4  738.75   171.5  738.33   211.9   737.2   242.2  736.46
   264.9  735.77   272.4  735.68   279.9  736.16   282.5  736.32   292.6  737.79
   302.7  738.96   312.8  739.43   322.9  741.48     333  747.36   343.1  753.81
   363.2  766.49   393.5  785.32   403.6  791.67   423.8  804.51
#Mann= 3 , 0 , 0
       0      .1       0   264.9    .045       0   279.9     .08       0
Bank Sta=264.9,279.9
XS Rating Curve= 0 ,0
Exp/Cntr=0.3,0.1

Type RM Length L Ch R = 1 ,3339.3  ,213.5,209.1,204.8
XS GIS Cut Line= 2
     1573504.291      388921.266     1573864.362      389317.991
#Sta/Elev= 30
    10.1  794.14    20.2  792.85    40.4  790.75    50.5  788.56    60.7  785.25
    80.9  777.36      91  772.93   121.3  758.88   141.5  750.38   151.6  746.77
   161.7  743.63   171.8  740.83     182  738.38   192.1   736.4   202.2  735.42
   242.6  734.62   305.9  731.37   313.4  731.05   320.9  731.31   323.5   731.4
   333.6  733.02   343.7  735.02   353.8  735.64   363.9  737.35     374  741.81
   394.2  753.95   454.9  791.33   495.3  814.88   515.5  826.38   535.8  837.63
#Mann= 3 , 0 , 0
       0      .1       0   305.9    .045       0   320.9     .08       0
Bank Sta=305.9,320.9
XS Rating Curve= 0 ,0
Exp/Cntr=0.3,0.1

Type RM Length L Ch R = 1 ,3130.2  ,238.1,237,235.8
XS GIS Cut Line= 2
     1573359.602      389149.738     1573724.582      389421.532
#Sta/Elev= 30
    10.1  826.99    50.6  799.95    60.7  793.39    70.8  786.99    80.9  780.84
      91  775.02   101.1  769.56   111.2   764.4   121.4  759.64   131.5  755.25
   141.6  751.22   151.7  747.61     182   737.5   192.1  734.67   202.3  733.26
   252.8  729.59   262.9  728.77     273  728.16   275.6  728.13   283.2  728.04
   290.6  728.39   293.3  728.53   313.5  730.13   323.6  731.31   333.7  734.01
   343.8  739.16   353.9  745.27   374.2  757.87   394.4  770.78   455.1   810.5
#Mann= 3 , 0 , 0
       0      .1       0   275.6    .045       0   290.6     .08       0
Bank Sta=275.6,290.6
XS Rating Curve= 0 ,0
Exp/Cntr=0.3,0.1

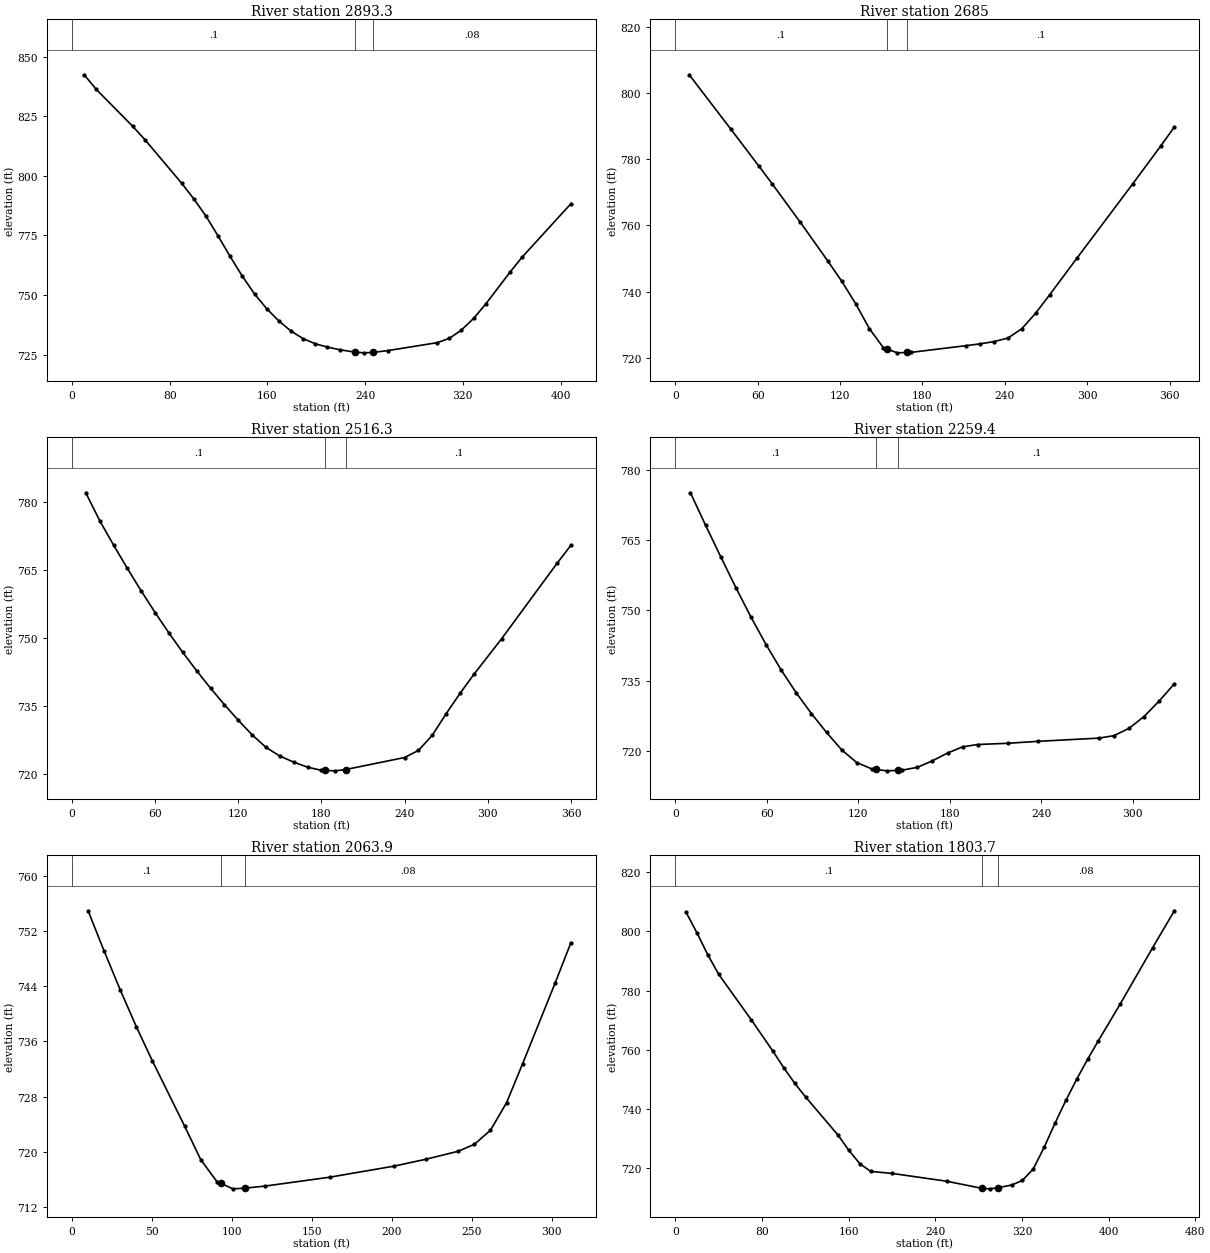
Type RM Length L Ch R = 1 ,2893.3  ,210.9,208.3,205.7
XS GIS Cut Line= 2
     1573227.587      389359.408     1573566.683      389587.197
#Sta/Elev= 30
      10  842.43    19.9  836.32    49.8  820.77    59.8  815.16    89.7  796.99
    99.6  790.45   109.6  783.21   119.6  774.81   129.5  766.18   139.5  757.87
   149.5  750.41   159.4  744.28   169.4  739.07   179.3  734.87   189.3  731.66
   199.3  729.49   209.2  728.13   219.2  727.01   231.6  726.02   239.1  725.71
   246.6   725.9     259  726.68   298.9  729.97   308.9  731.77   318.8  735.26
   328.8  740.14   338.8  746.24   358.7  759.63   368.6  765.92   408.5  788.32
#Mann= 3 , 0 , 0
       0      .1       0   231.6    .045       0   246.6     .08       0
Bank Sta=231.6,246.6
XS Rating Curve= 0 ,0
Exp/Cntr=0.3,0.1

Type RM Length L Ch R = 1 ,2685    ,167,168.7,170.4
XS GIS Cut Line= 2
     1573147.344      389574.254     1573470.908      389739.919
#Sta/Elev= 25
    10.1  805.48    40.4  789.07    60.6  778.04    70.7  772.46    90.9  761.02
   111.1  749.22   121.2  743.15   131.3  736.38   141.4   728.8   151.5  723.08
   154.1  722.68   161.6  721.52   169.1  721.63   171.7  721.66     212   723.7
   222.1  724.24   232.2  724.92   242.3     726   252.4  728.81   262.5  733.52
   272.6  739.01   292.8  750.26   333.2  772.56   353.4  783.89   363.5   789.7
#Mann= 3 , 0 , 0
       0      .1       0   154.1    .045       0   169.1      .1       0
Bank Sta=154.1,169.1
XS Rating Curve= 0 ,0
Exp/Cntr=0.3,0.1

Type RM Length L Ch R = 1 ,2516.3  ,243.8,256.9,266.5
XS GIS Cut Line= 2
     1573069.688      389706.268     1573377.721      389892.641
#Sta/Elev= 30
      10  781.94      20  775.82      30  770.46      40  765.29      50  760.34
      60  755.59      70  751.09      80   746.8      90  742.78     100  738.94
     110  735.32     120  731.89     130  728.69     140  725.92     150  724.01
     160  722.67     170  721.57     180  720.87   182.5  720.85     190  720.76
   197.5  721.05     240  723.69     250  725.25     260  728.61     270  733.35
     280  737.81     290     742     310  749.83     350  766.43     360   770.4
#Mann= 3 , 0 , 0
       0      .1       0   182.5    .045       0   197.5      .1       0
Bank Sta=182.5,197.5
XS Rating Curve= 0 ,0
Exp/Cntr=0.3,0.1

Type RM Length L Ch R = 1 ,2259.4  ,189.8,195.5,195.8
XS GIS Cut Line= 2
      1572988.86      389769.014     1573216.056      390004.688
#Sta/Elev= 30
     9.9  775.06    19.8  768.16    29.8  761.39    39.7  754.83    49.6  748.55
    59.5  742.68    69.4  737.26    79.4  732.34    89.3  727.93    99.2  723.92
   109.1  720.22     119   717.5     129  716.12   131.4  716.03   138.9  715.73
   146.4  715.84   148.8  715.88   158.7  716.47   168.6  717.86   178.6  719.53
   188.5  720.85   198.4  721.35   218.2  721.61   238.1  722.03   277.8  722.71
   287.7  723.23   297.6  724.79   307.5  727.32   317.4  730.62   327.4   734.3
#Mann= 3 , 0 , 0
       0      .1       0   131.4    .045       0   146.4      .1       0
Bank Sta=131.4,146.4
XS Rating Curve= 0 ,0
Exp/Cntr=0.3,0.1

Type RM Length L Ch R = 1 ,2063.9  ,259,260.2,261.4
XS GIS Cut Line= 2
     1572888.492      389846.048     1573092.985      390081.603
#Sta/Elev= 22
    10.1  754.91    20.1   749.1    30.2  743.46    40.2  738.16    50.3  733.18
    70.4  723.77    80.5  718.91    90.6  715.73    93.1  715.47   100.6  714.68
   108.1  714.78   120.7  715.08     161  716.36   201.2  717.96   221.4  718.97
   241.5  720.12   251.6  721.13   261.6  723.16   271.7  727.16   281.7  732.79
   301.9  744.39   311.9  750.31
#Mann= 3 , 0 , 0
       0      .1       0    93.1    .045       0   108.1     .08       0
Bank Sta=93.1,108.1
XS Rating Curve= 0 ,0
Exp/Cntr=0.3,0.1

Type RM Length L Ch R = 1 ,1803.7  ,218.3,208.3,198.4
XS GIS Cut Line= 2
     1572606.344      389858.991     1572880.727      390229.148
#Sta/Elev= 30
      10  806.41      20   799.5      30  792.09    40.1  785.48    70.1  770.17
    90.1  759.58   100.2  753.93   110.2  748.74   120.2  744.14   150.2  731.25
   160.3  726.04   170.3  721.61   180.3  718.98   200.3  718.29   250.4  715.67
     283  713.27   290.5  713.09     298  713.46   310.5  714.37   320.5  715.93
   330.5  719.81   340.6  727.14   350.6  735.27   360.6  742.94   370.6   750.1
   380.6  756.78   390.6  763.09   410.7  775.44   440.7   794.5   460.8  806.98
#Mann= 3 , 0 , 0
       0      .1       0     283    .045       0     298     .08       0
Bank Sta=283,298
XS Rating Curve= 0 ,0
Exp/Cntr=0.3,0.1

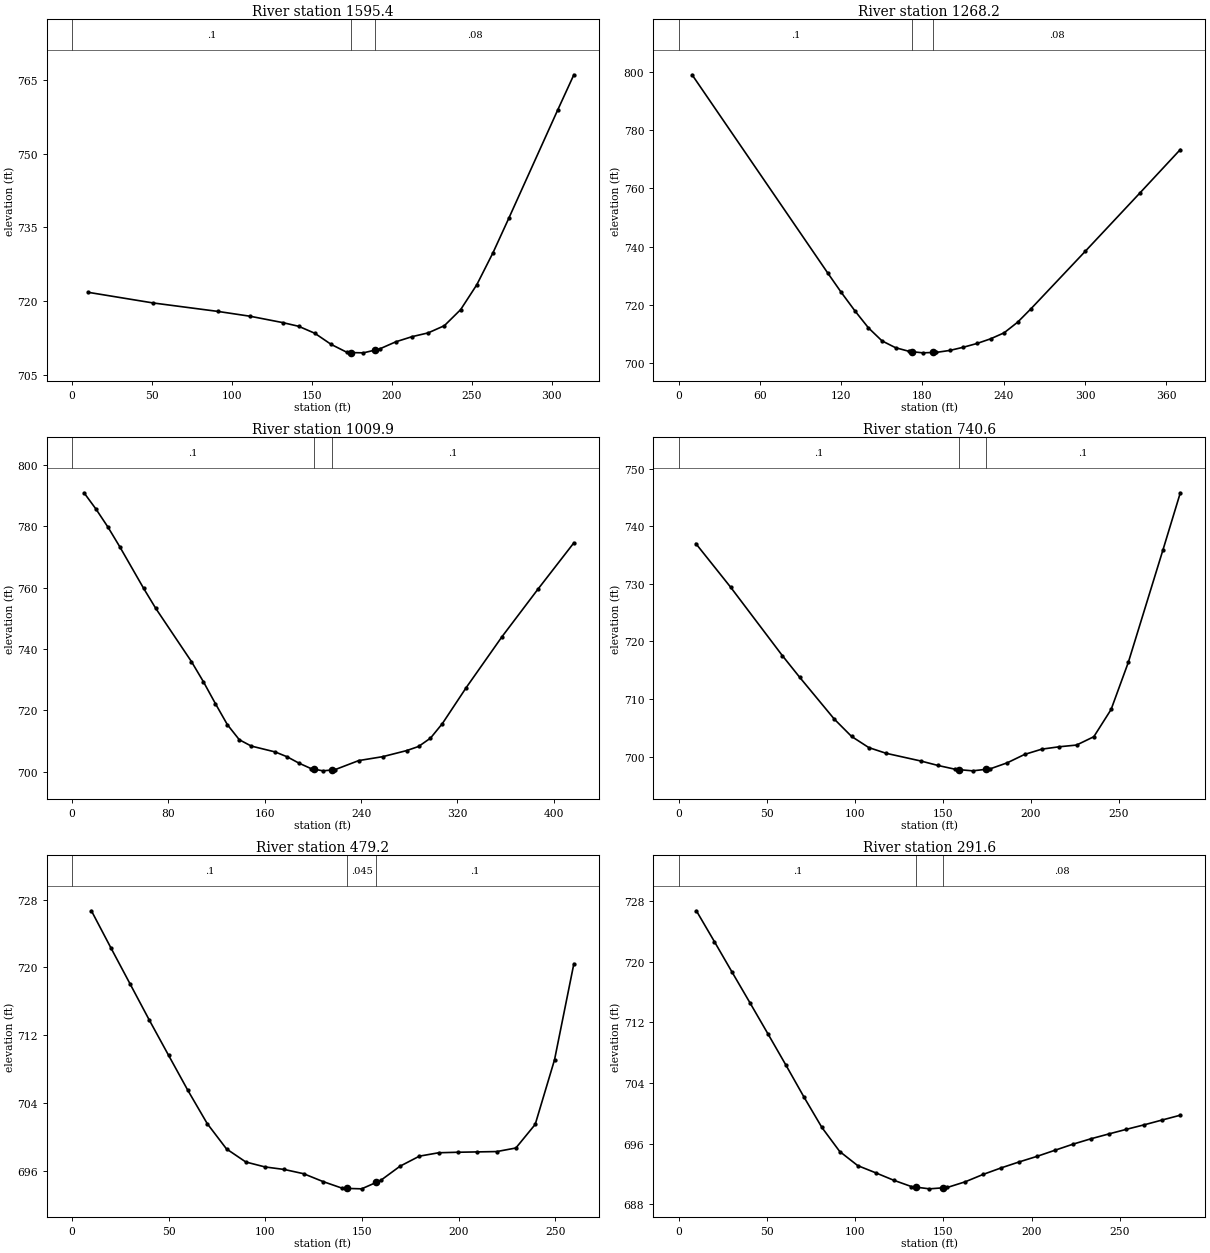
Type RM Length L Ch R = 1 ,1595.4  ,327.8,327.2,326.6
XS GIS Cut Line= 2
     1572448.445      390112.665     1572725.416       390260.21
#Sta/Elev= 23
    10.1   721.8    50.6  719.64    91.1  717.92   111.4  716.93   131.6  715.65
   141.7  714.89   151.8  713.47     162  711.21   172.1  709.56   174.7  709.54
   182.2  709.49   189.7  710.07   192.3  710.28   202.5  711.74   212.6  712.78
   222.7  713.55   232.8  715.01     243  718.28   253.1  723.34   263.2  729.83
   273.3     737   303.7  758.89   313.8  766.05
#Mann= 3 , 0 , 0
       0      .1       0   174.7    .045       0   189.7     .08       0
Bank Sta=174.7,189.7
XS Rating Curve= 0 ,0
Exp/Cntr=0.3,0.1

Type RM Length L Ch R = 1 ,1268.2  ,265.3,258.3,251.3
XS GIS Cut Line= 2
     1572251.718      390379.282     1572583.048      390544.947
#Sta/Elev= 22
      10  798.92   110.1  730.94   120.1  724.28   130.2  717.93   140.2  712.09
   150.2  707.63   160.2  705.29   170.2  704.04   172.7  703.91   180.2  703.53
   187.7  703.65   190.2  703.68   200.2  704.35   210.2  705.45   220.3  706.74
   230.3  708.33   240.3  710.39   250.3  714.04   260.3  718.72   300.4  738.45
   340.4  758.29   370.4  773.28
#Mann= 3 , 0 , 0
       0      .1       0   172.7    .045       0   187.7     .08       0
Bank Sta=172.7,187.7
XS Rating Curve= 0 ,0
Exp/Cntr=0.3,0.1

Type RM Length L Ch R = 1 ,1009.9  ,262.1,269.3,276.5
XS GIS Cut Line= 2
     1572095.333      390660.846     1572507.339      390723.579
#Sta/Elev= 30
     9.9  790.84    19.8  785.57    29.8  779.67    39.7  773.22    59.5  759.69
    69.5  753.22    99.2  735.87   109.1  729.33   119.1  722.18     129  715.36
   138.9  710.46   148.8   708.4   168.7  706.48   178.6  704.91   188.5  702.83
   198.5  701.06   200.9  700.88   208.4  700.33   215.9  700.61   218.3   700.7
   238.1  703.67     258  704.94   277.8  706.91   287.8  708.26   297.7  710.97
   307.6  715.72   327.4  727.43   357.2  744.04     387  759.48   416.8  774.54
#Mann= 3 , 0 , 0
       0      .1       0   200.9    .045       0   215.9      .1       0
Bank Sta=200.9,215.9
XS Rating Curve= 0 ,0
Exp/Cntr=0.3,0.1

Type RM Length L Ch R = 1 ,740.6   ,265.4,261.4,257.3
XS GIS Cut Line= 2
     1572098.996      390878.865      1572352.67      391008.291
#Sta/Elev= 25
     9.8  737.02    29.5  729.46    58.9  717.55    68.7   713.8    88.4  706.51
    98.2   703.5     108  701.56   117.8  700.57   137.5  699.23   147.3  698.45
   157.1  697.79   159.4  697.72   166.9  697.52   174.4  697.78   176.8  697.86
   186.6  698.92   196.4  700.37   206.2  701.29     216   701.7   225.9     702
   235.7  703.45   245.5  708.18   255.3  716.39     275  735.97   284.8  745.84
#Mann= 3 , 0 , 0
       0      .1       0   159.4    .045       0   174.4      .1       0
Bank Sta=159.4,174.4
XS Rating Curve= 0 ,0
Exp/Cntr=0.3,0.1

Type RM Length L Ch R = 1 ,479.2   ,180.8,187.6,194.5
XS GIS Cut Line= 2
     1572005.809      391153.248     1572254.306      391228.314
#Sta/Elev= 28
      10  726.68      20  722.35      30  718.07    39.9  713.83    49.9  709.67
    59.9  705.53    69.9  701.62    79.9  698.63    89.9  697.09    99.8  696.51
   109.8  696.21   119.8  695.71   129.8  694.79   139.8     694   142.3  693.98
   149.8  693.93   157.3  694.68   159.7  694.93   169.7   696.6   179.7  697.78
   189.7  698.18   199.7  698.24   209.7  698.28   219.7  698.32   229.6  698.74
   239.6  701.52   249.6  709.13   259.6  720.44
#Mann= 3 , 0 , 0
       0      .1       0   142.3    .045       0   157.3      .1       0
Bank Sta=142.3,157.3
XS Rating Curve= 0 ,0
Exp/Cntr=0.3,0.1

Type RM Length L Ch R = 1 ,291.6   ,144.9,145.1,145.4
XS GIS Cut Line= 2
     1571938.508      391274.908      1572171.63      391437.383
#Sta/Elev= 30
    10.1  726.69    20.3  722.63    30.4  718.57    40.6   714.5    50.7  710.44
    60.9  706.31      71  702.15    81.2  698.12    91.3  694.95   101.5  693.09
   111.6  692.15   121.8  691.17   131.9  690.33   134.6  690.25   142.1  690.03
   149.6  690.16   152.2  690.21   162.4  690.96   172.5  691.93   182.7  692.79
   192.8  693.57     203  694.31   213.1  695.11   223.3  695.91   233.4  696.62
   243.6  697.26   253.7  697.88   263.9  698.48     274  699.11   284.2  699.74
#Mann= 3 , 0 , 0
       0      .1       0   134.6    .045       0   149.6     .08       0
Bank Sta=134.6,149.6
XS Rating Curve= 0 ,0
Exp/Cntr=0.3,0.1

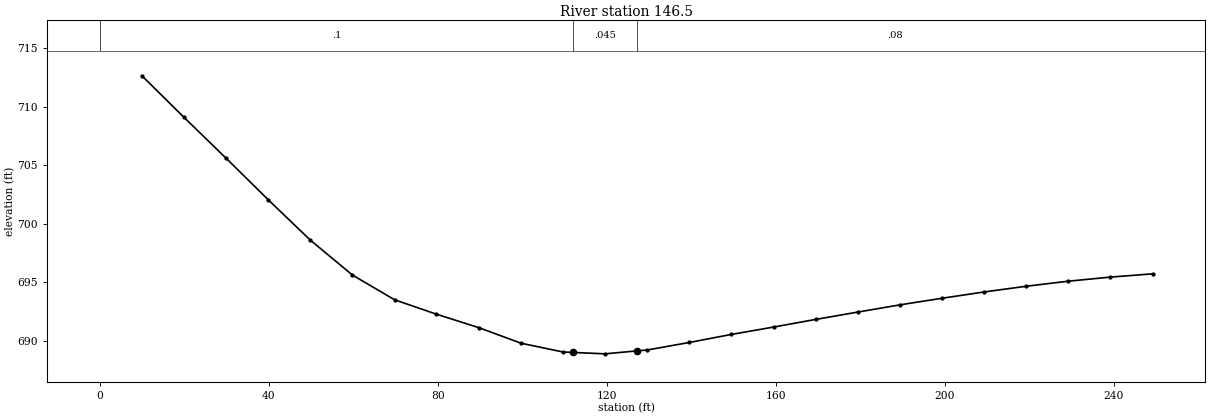
Type RM Length L Ch R = 1 ,146.5   ,148.1,146.5,144.9
XS GIS Cut Line= 2
     1571864.001      391396.312     1572068.493       391538.68
#Sta/Elev= 27
      10  712.63    19.9   709.1    29.9  705.59    39.9  702.03    49.8   698.6
    59.8   695.6    69.8  693.48    79.7  692.25    89.7   691.1    99.7  689.77
   109.6  689.02   112.1  688.98   119.6  688.86   127.1  689.11   129.6  689.19
   139.5  689.83   149.5  690.52   159.5  691.15   169.4   691.8   179.4  692.43
   189.4  693.05   199.3  693.61   209.3  694.15   219.3  694.64   229.2  695.07
   239.2  695.42   249.2   695.7
#Mann= 3 , 0 , 0
       0      .1       0   112.1    .045       0   127.1     .08       0
Bank Sta=112.1,127.1
XS Rating Curve= 0 ,0
Exp/Cntr=0.3,0.1

Chan Stop Cuts=-1
Use User Specified Reach Order=0